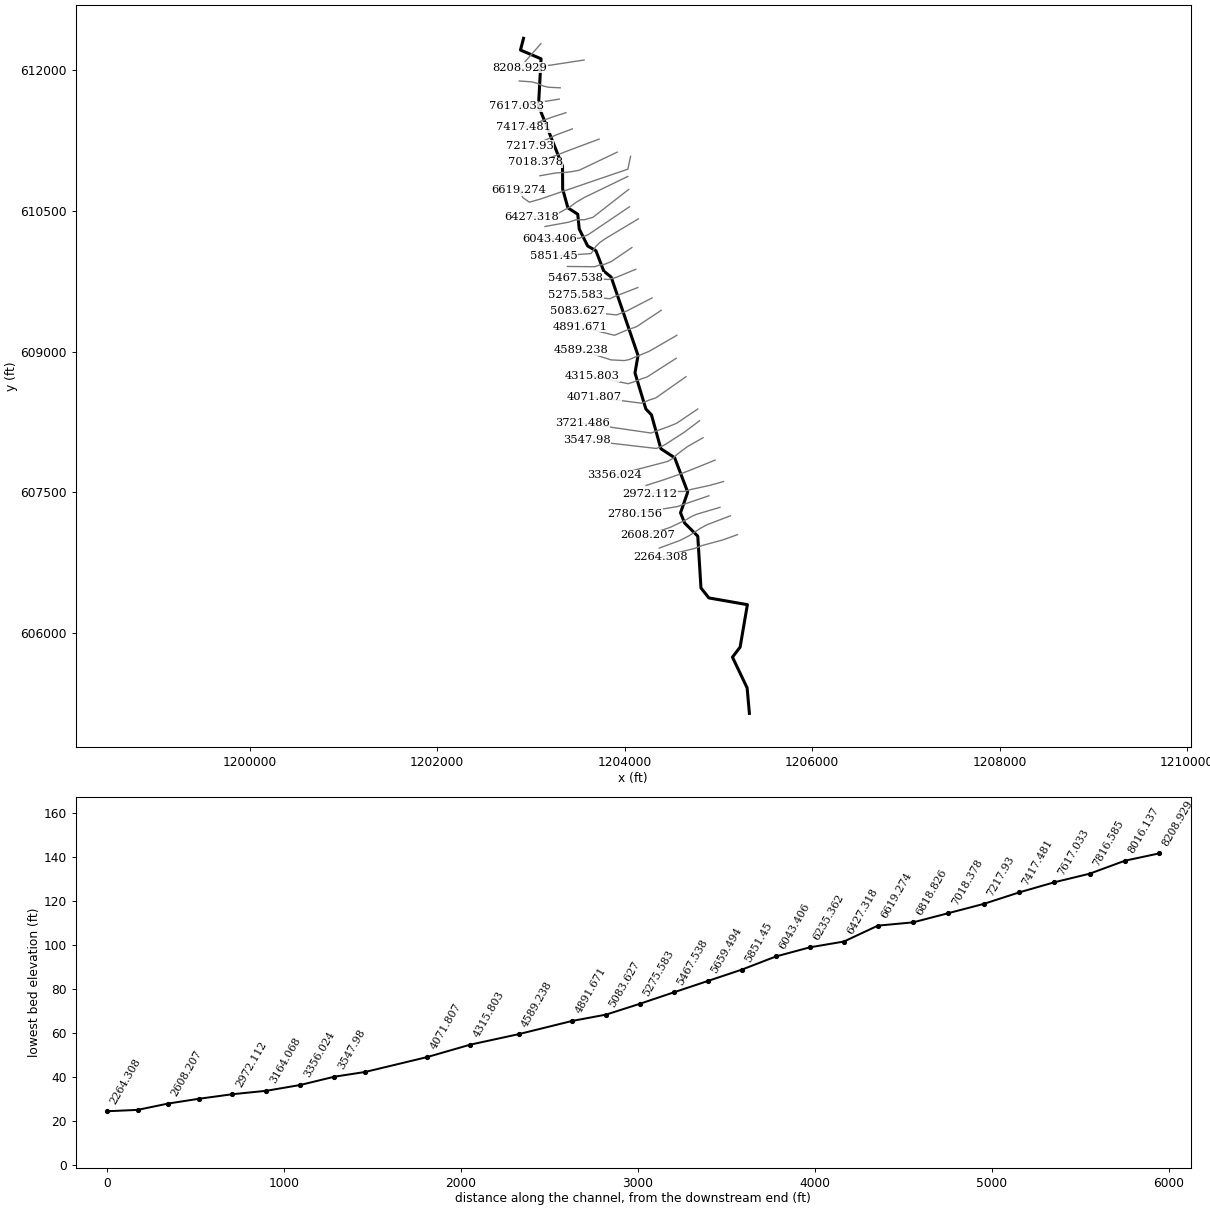
--- 39_ras.prj (project) ---

Proj Title=39
Current Plan=p01
Default Exp/Contr=0.3,0.1
English Units
Geom File=g01
Flow File=f01
Plan File=p01
Y Axis Title=Elevation
X Axis Title(PF)=Main Channel Distance
X Axis Title(XS)=Station
BEGIN DESCRIPTION:
RFD model 39 exported to HEC-RAS
END DESCRIPTION:

--- 39_ras.p01 (plan) ---

Plan Title=Plan 01
Program Version=4.10
Short Identifier=Plan 01
Geom File=g01
Flow File=f01
Subcritical Flow
Calc Critical at every XS
Secant Critical Depth

--- 39_ras.f01 (steady flow) ---

Flow Title=Flow 01
Program Version=4.10
Number of Profiles= 5
Profile Names=10yr,25yr,50yr,100yr,500yr
River Rch & RM=39,39,8208.929
     568     718     867     990    1238
River Rch & RM=39,39,4891.671
  606.05  772.87  935.46 1067.52  1365.1
River Rch & RM=39,39,4589.238
   617.3  789.34  955.98 1093.91 1403.74
River Rch & RM=39,39,4315.803
   620.7  794.32  962.19 1101.92 1415.49
River Rch & RM=39,39,4071.807
  623.24  798.04  966.82 1107.88 1424.25
River Rch & RM=39,39,3721.486
  635.66   816.3   989.6  1137.3 1467.56
River Rch & RM=39,39, 3547.98
  641.74  825.25 1000.76 1151.75 1488.89
River Rch & RM=39,39,3356.024
  643.34  827.62 1003.72 1155.58 1494.54
River Rch & RM=39,39,3164.068
   670.5  867.78 1053.87 1220.77 1591.29
River Rch & RM=39,39,2972.112
  681.27  883.78 1073.87 1246.87 1630.23
River Rch & RM=39,39,2780.156
   683.1   886.5 1077.27 1251.31 1636.88
River Rch & RM=39,39,2608.207
  706.95  922.06 1121.75 1309.61 1724.32
River Rch & RM=39,39,2436.257
   710.4  927.22 1128.22 1318.11 1737.12
River Rch & RM=39,39,2264.308
  728.62  954.53 1162.43 1363.17 1805.16
River Rch & RM=39,39,2092.358
  730.94  958.01 1166.78 1368.92 1813.86
River Rch & RM=39,39,  1867.1
   736.5  966.37 1177.27 1382.77 1834.86
River Rch & RM=39,39,1215.453
  744.58  978.52  1192.5 1402.93 1865.45
River Rch & RM=39,39,893.1167
  751.57  989.07 1205.72 1420.44  1892.1
Boundary for River Rch & Prof#=39,39,1
Up Type= 0
Dn Type= 2
Boundary for River Rch & Prof#=39,39,2
Up Type= 0
Dn Type= 2
Boundary for River Rch & Prof#=39,39,2
Up Type= 0
Dn Type= 2
Boundary for River Rch & Prof#=39,39,2
Up Type= 0
Dn Type= 2
Boundary for River Rch & Prof#=39,39,2
Up Type= 0
Dn Type= 2

--- 39_ras.g01 (geometry) ---

Geom Title=39
Program Version=4.10

River Reach=39,39
Reach XY= 30
1202920.99585417612342.8491809371202888.49586016612217.849218979
1203107.98184112612124.525256783 1203080.7595197611623.456561804
1203337.00814342 610978.339731411203338.67480254610734.173137248
1203394.50811371 610534.173194991203499.50808075610465.839878902
1203515.34140477610308.3399252441203605.34137303610127.506642982
 1203693.6746788610075.8399891411203777.00798127609860.006717473
1203856.17462274609795.0067345051204142.84118062608959.173641101
1204110.28106892608772.404217094 1204226.1744729608388.340474874
1204286.17445335608325.0071586221204386.17441341607964.173929557
 1204533.6743671607867.5072873091204672.84098208607500.840725526
1204596.17433169607280.0074600131204639.50764909607171.674157575
1204780.34093678607030.0075289311204814.50757742606477.507691979
1204898.67421615606371.6743876491205309.58246675606299.696509287
1205232.00761342605846.3903613691205150.34096777605739.723728701
1205307.00757876605411.3904883561205331.17423043605139.723901674

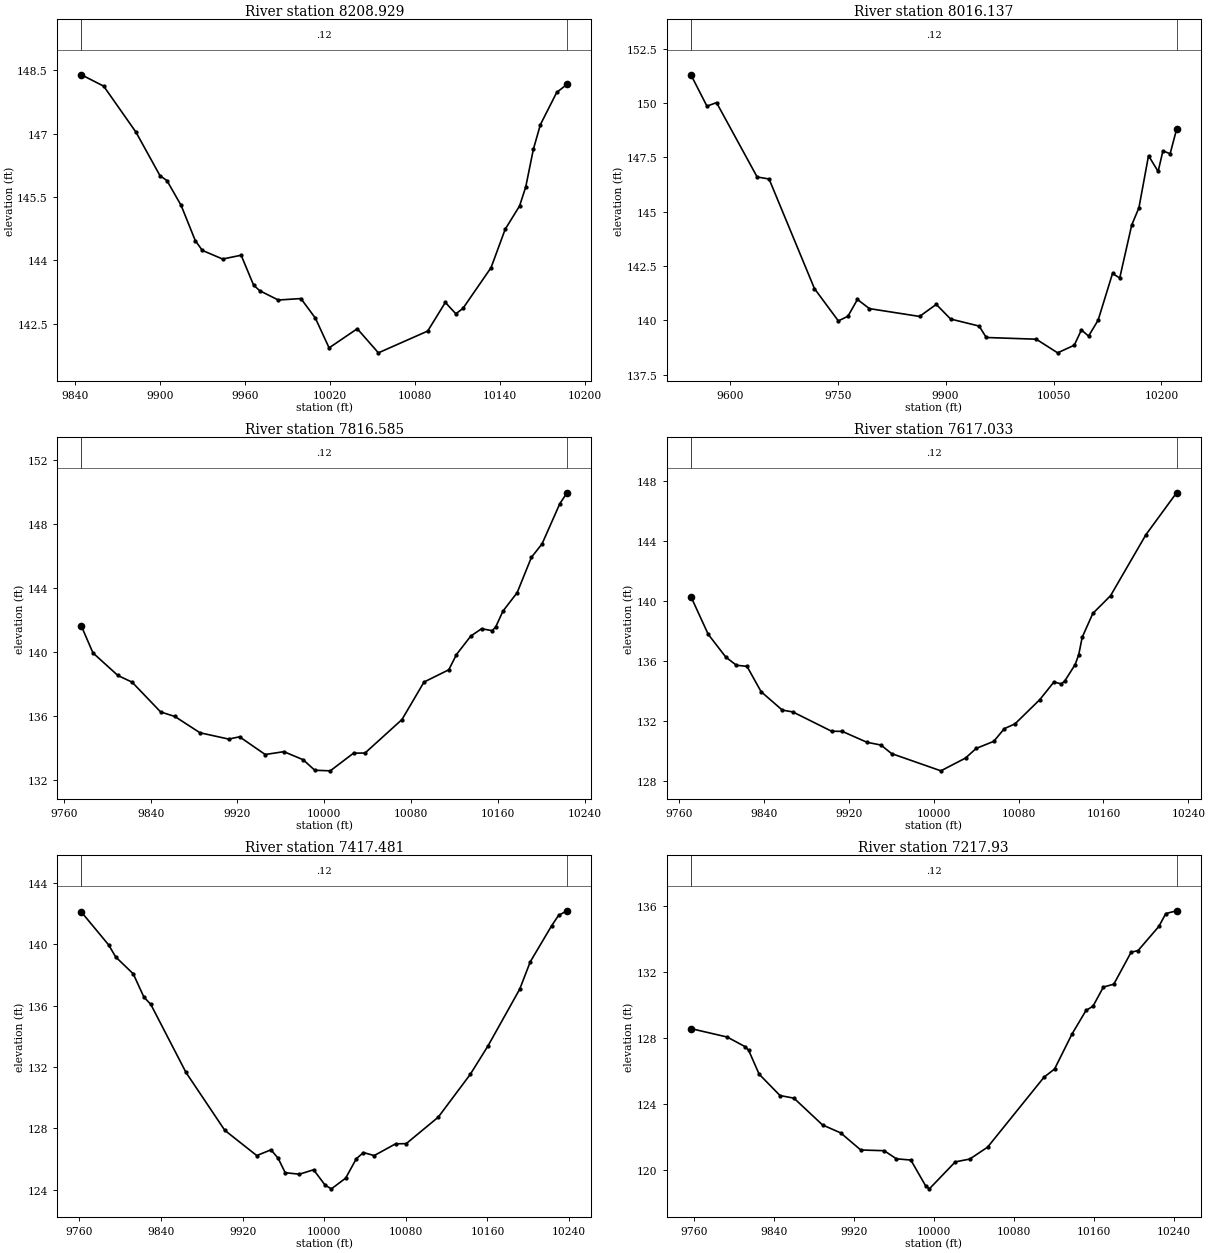
Type RM Length L Ch R = 1 ,8208.929,192.791800,192.791800,192.791800
XS GIS Cut Line= 2
1203106.00948119612285.5745120641202879.78894246612028.031129524
#Sta/Elev= 30
9844.745148.39739860.481148.12819883.275147.03839900.253146.00639905.109145.8929
9915.167145.3022 9925.11144.47219930.081144.2394 9944.41144.0345 9957.51144.1245
9966.244143.41969970.611143.28399983.711 143.0649999.681143.098710009.91142.6341
10019.57141.930810039.45142.383910054.37141.813310089.17 142.32910101.61143.0071
10109.05142.737510114.02142.864710133.91143.832210143.85144.739310154.02145.2918
10158.38145.744210163.74146.633610168.71147.216810180.22147.979410187.53148.1725
#Mann= 3 , 0 , 0
9844.745    0.12       09844.745    0.12       010187.53    0.12       0
#XS Ineff= 2 , 0
       0                               0
Bank Sta=9844.745,10187.53
Exp/Cntr=0.3,0.1

Type RM Length L Ch R = 1 ,8016.137,199.551900,199.551900,199.551900
XS GIS Cut Line= 6
1203567.15134862612111.5587130491203217.25231844612058.007626638
1203119.05941445612045.9840264321203117.07565108612045.729697838
1203012.76549423612032.8285346481202899.79367071612012.060456172
#Sta/Elev= 30
  9546.1151.3067 9568.41149.86059581.686150.0261 9638.11146.60159654.705146.5082
9717.767141.46279750.957139.97469764.233140.18759777.509140.96149794.104140.5405
9863.804140.17989887.037140.73589906.923140.06119946.587139.73679956.503139.2106
10025.92139.131810055.67138.504210078.81138.855610088.73139.560410098.65139.2744
10111.92 140.00610131.94142.157410141.95141.949210158.63144.391510168.63145.1814
10181.98147.581610195.32146.855210201.99147.8036   10212147.670210220.97 148.798
#Mann= 3 , 0 , 0
  9546.1    0.12       0  9546.1    0.12       010220.97    0.12       0
#XS Ineff= 2 , 0
       09950.807                       0
Bank Sta=9546.1,10220.97
Exp/Cntr=0.3,0.1

Type RM Length L Ch R = 1 ,7816.585,199.552000,199.552000,199.552000
XS GIS Cut Line= 6
1203312.99867052611814.8029749921203185.89200929 611821.10752206
1203132.39321368611833.7670883051203062.57310444611863.660805768
1203011.19032955611877.9603295821202875.73077571611887.897676999
#Sta/Elev= 30
9776.083141.61039786.765139.93769809.731138.53049822.854138.11389849.122136.2576
9862.314135.97219885.401134.95759911.904134.5631 9921.94134.70529945.581133.6004
9962.808133.77799980.594133.27399991.265132.619210005.58 132.58210027.05 133.686
10037.62133.692210071.68135.782110092.02 138.12210114.84138.885610121.94139.8384
10135.14140.989710145.03141.445210154.93141.327210158.21141.570910164.77142.5433
 10177.9143.698810191.02145.897910200.87146.744310217.27149.253110223.91149.9284
#Mann= 3 , 0 , 0
9776.083    0.12       09776.083    0.12       010223.91    0.12       0
#XS Ineff= 2 , 0
       0                               0
Bank Sta=9776.083,10223.91
Exp/Cntr=0.3,0.1

Type RM Length L Ch R = 1 ,7617.033,199.551900,199.551900,199.551900
XS GIS Cut Line= 5
1203301.99791895611694.5387180791203077.03637834611657.767977186
1203075.05513608611657.4947023911203027.10536229611650.134205218
1202850.67878467611617.372016151
#Sta/Elev= 30
9771.053140.31029787.352137.79629803.974136.27269813.947  135.73 9823.92135.6575
9837.217 133.9679857.164132.73899867.137132.61579903.705131.32629913.678131.3198
9936.948130.59229950.246130.40569960.219129.836910006.74128.685510029.98129.5399
10039.94130.178210056.57130.653510066.58131.501710076.59131.817810099.95133.4332
 10113.3134.613610119.97134.490110123.31134.654510133.32135.777610136.66136.4294
10139.99 137.603   10150139.188610166.69140.368210200.06144.441510228.95147.2361
#Mann= 3 , 0 , 0
9771.053    0.12       09771.053    0.12       010228.95    0.12       0
#XS Ineff= 2 , 0
       0                               0
Bank Sta=9771.053,10228.95
Exp/Cntr=0.3,0.1

Type RM Length L Ch R = 1 ,7417.481,199.552000,199.552000,199.552000
XS GIS Cut Line= 6
1203373.71071405611549.5125565831203248.11298113611509.364902337
1203149.11615616 611474.040791321203147.25055988611473.319992814
1203028.42593302611430.1184542671202923.70071444611394.727832669
#Sta/Elev= 30
9762.031142.11079788.763139.96549795.651139.18159812.873138.07779823.206136.5753
9830.095136.08169864.539131.64839902.524127.87739933.875126.22839947.808 126.601
9954.775126.05929961.742125.11149975.676125.0123 9989.61125.3012   10001124.2874
10007.06124.057910021.02 124.755 10031.5126.027810038.48126.425110048.95126.2264
 10069.9126.992810080.37127.006310111.79128.736210143.08 131.521 10160.4133.3695
10191.56137.079310201.95138.870910222.73141.202210229.66141.894210237.98142.1929
#Mann= 3 , 0 , 0
9762.031    0.12       09762.031    0.12       010237.98    0.12       0
#XS Ineff= 2 , 0
       0                               0
Bank Sta=9762.031,10237.98
Exp/Cntr=0.3,0.1

Type RM Length L Ch R = 1 , 7217.93,199.551900,199.551900,199.551900
XS GIS Cut Line= 6
 1203442.0666213611376.4237590551203276.28961489611315.182256798
1203237.52085758611298.0516722271203188.50859022611272.420160537
1203143.80748342 611253.553064371202990.27142024611198.749616644
#Sta/Elev= 30
    9757128.57899793.266 128.0679811.325127.47899814.808127.25549825.258  125.81
9846.158124.51179860.101 124.351 9888.72122.72429906.901122.23959926.942121.2025
9950.362121.15949962.677120.66499977.056120.59149991.909119.02129995.622118.8415
10021.52 120.47910036.11120.652210053.91121.376210110.37125.627510120.88 126.122
10138.38128.252810152.39129.684110159.35129.940410169.75131.104310180.16131.2785
10197.51133.221310204.45  133.3210225.26134.7882 10232.2135.5693   10243 135.739
#Mann= 3 , 0 , 0
    9757    0.12       0    9757    0.12       0   10243    0.12       0
#XS Ineff= 2 , 0
       0                               0
Bank Sta=9757,10243
Exp/Cntr=0.3,0.1

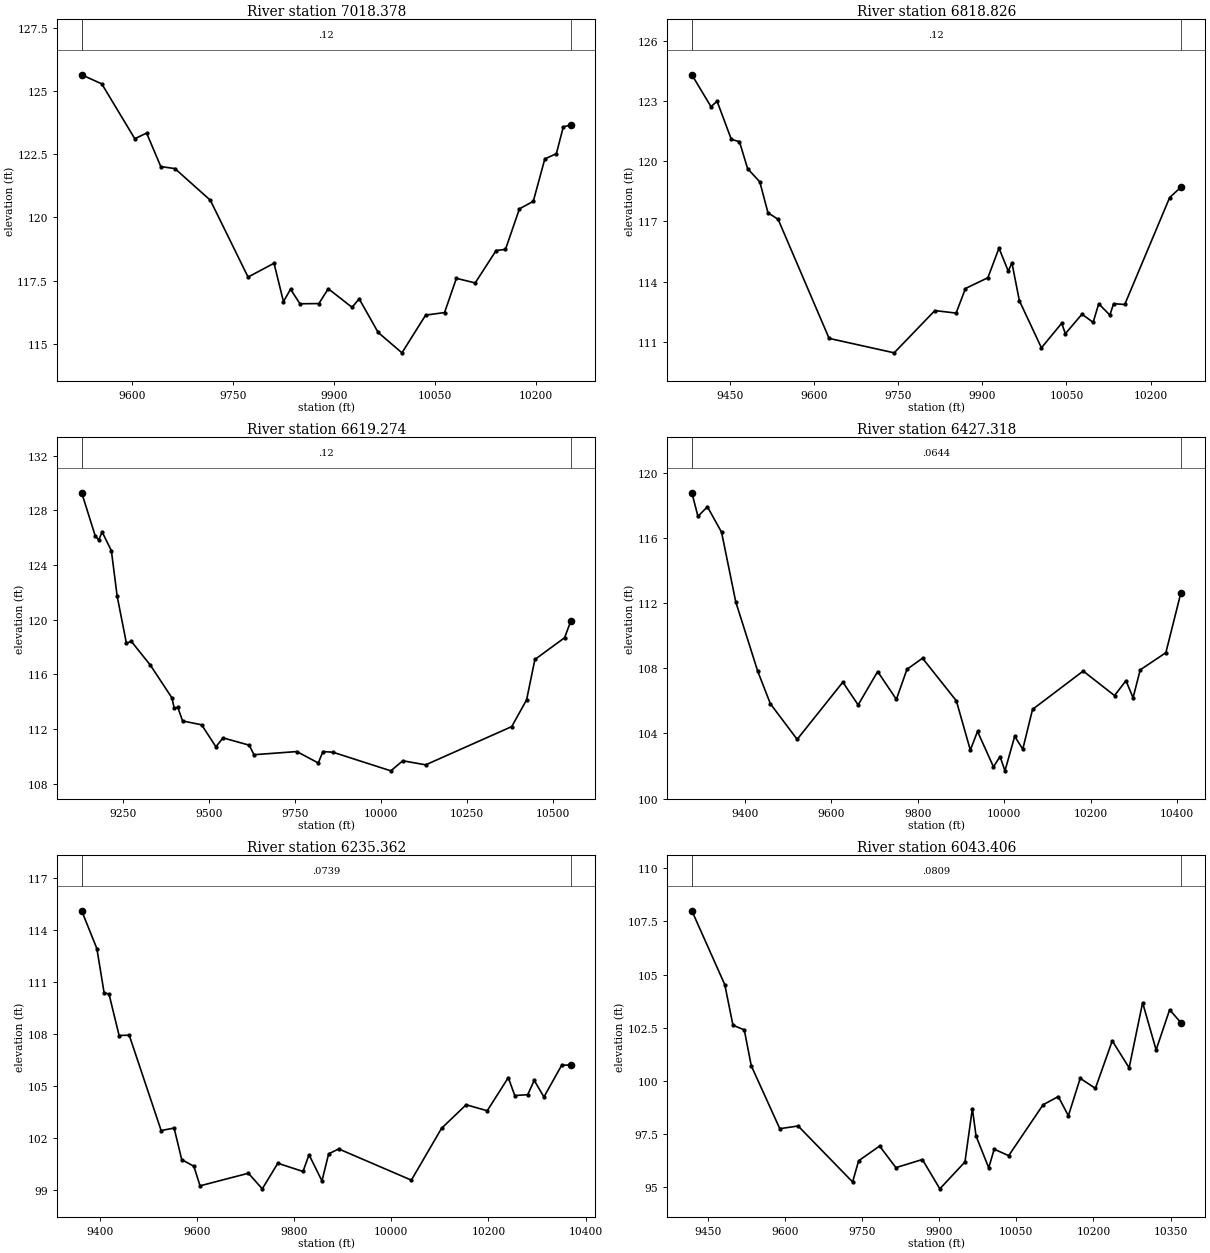
Type RM Length L Ch R = 1 ,7018.378,199.552000,199.552000,199.552000
XS GIS Cut Line= 6
1203727.24588367 611267.58208783  1203382.399986611138.630230829
1203282.80811629611099.2123253491203193.57467657611065.052609667
1203123.66026953 611041.652935551203045.62028751611017.991734043
#Sta/Elev= 30
9525.723125.65229555.561125.29129604.599123.11739622.113123.34399643.129122.0156
9664.145121.93449716.686120.68189772.729117.63669811.259118.1844 9825.27116.6626
9835.778117.15569849.789116.57819877.811116.58679891.821117.17419927.084116.4378
9937.667116.77339965.889115.441410001.19114.634210036.32116.128410064.42116.2302
10081.99117.586910109.89117.404610141.02118.688810154.86118.732810175.57120.3403
10196.14 120.63710213.28122.318710230.43122.525410240.71123.588310251.82123.6641
#Mann= 3 , 0 , 0
9525.723    0.12       09525.723    0.12       010251.82    0.12       0
#XS Ineff= 2 , 0
       09794.201                       0
Bank Sta=9525.723,10251.82
Exp/Cntr=0.3,0.1

Type RM Length L Ch R = 1 ,6818.826,199.551900,199.551900,199.551900
XS GIS Cut Line= 6
1203920.40342063611128.3694486171203515.38706467610935.530727267
1203442.96336102610921.7652018371203384.72123453610914.405670345
1203267.23830739610906.6526139531203095.48746905610876.411262512
#Sta/Elev= 30
9381.164124.30389415.296122.71569426.198 122.9849451.634121.08539466.169120.9696
9480.704119.62679502.506118.96559517.041117.4271 9535.21117.09919626.198111.1686
9742.332 110.4489815.007112.55389852.935112.42899869.633113.65349909.647114.1904
9929.488115.66559946.023114.52079952.637114.9298 9965.84113.049210005.25110.6973
10041.41 111.92210048.01111.402810077.68112.374810097.58 111.96710107.54112.8938
10127.45112.328910134.09112.896510154.01112.8573 10234.2118.185110254.38 118.705
#Mann= 3 , 0 , 0
9381.164    0.12       09381.164    0.12       010254.38    0.12       0
#XS Ineff= 2 , 0
       09927.825                       0
Bank Sta=9381.164,10254.38
Exp/Cntr=0.3,0.1

Type RM Length L Ch R = 1 ,6619.274,191.955900,191.955900,191.955900
XS GIS Cut Line= 6
1204063.25939721611084.523220405 1204034.4275724610947.017594203
1203100.72001383610627.6496882141202983.17488176610594.382197991
1202914.42206863610643.1745169611202874.50108039 610720.79866077
#Sta/Elev= 30
9130.963129.29329170.325126.13959180.382125.83559190.439126.42159217.256125.0523
9234.017121.72639260.834118.29279275.428118.40889330.761 116.667 9393.01114.2879
9399.927113.52219410.302113.58349424.135112.59069479.468112.30819520.968110.6992
9541.717111.3512  9617.8110.81699631.633110.11919756.132 110.3499818.382109.5142
9832.215110.3527 9861.07110.299710029.34108.938110063.92109.674410130.56109.3775
10380.56112.176810423.71114.132610447.85117.090210534.16118.681910552.15119.9029
#Mann= 3 , 0 , 0
9130.963    0.12       09130.963    0.12       010552.15    0.12       0
#XS Ineff= 2 , 0
       09883.097        10107.81       0
Bank Sta=9130.963,10552.15
Exp/Cntr=0.3,0.1

Type RM Length L Ch R = 1 ,6427.318,191.955900,191.955900,191.955900
XS GIS Cut Line= 6
1204033.51368997610869.0859080851203567.90613177610643.855935812
1203480.48760426610592.2777935271203416.45711952610544.075015053
1203273.06464824 610465.36925438 1203005.0803178610437.526726529
#Sta/Elev= 30
9277.185118.75939291.287117.31249313.154117.90329345.955116.33829378.755112.0688
9429.779107.80049458.935105.81669520.892103.63419626.583107.14369662.007105.7492
9707.212107.79319750.497 106.087 9775.02107.93159811.023108.61199889.348105.9977
9921.655102.9747 9938.31104.12159975.269101.94569990.447102.581210001.83101.7038
10024.35103.822510043.07103.035710065.65105.473110182.88107.824810255.44106.3206
10281.83107.234210298.32106.187710314.82107.896610374.19108.949710409.15 112.642
#Mann= 3 , 0 , 0
9277.185  0.0644       09277.185  0.0644       010409.15  0.0644       0
#XS Ineff= 2 , 0
       09831.009                       0
Bank Sta=9277.185,10409.15
Exp/Cntr=0.3,0.1

Type RM Length L Ch R = 1 ,6235.362,191.955800,191.955800,191.955800
XS GIS Cut Line= 6
1204042.21447992610729.873268887 1203661.6656982  610433.3211184
1203570.96342155610407.3438850791203479.50256711610405.603849262
1203400.85624006610380.7397929131203149.51343098610334.857405111
#Sta/Elev= 30
9362.845115.10659394.129112.92459408.987 110.3849419.085110.30419439.882107.9176
9460.679107.93729526.412102.43919553.099102.58279568.823100.76119593.779100.3819
9606.47499.252869706.082 99.97899734.57499.079159766.599100.55469818.385100.0798
9830.863101.04259857.45499.53555 9871.23 101.0969891.894  101.3810041.4899.58015
10103.71102.571410154.31103.926510197.67103.579410241.02105.489210254.36104.4584
10281.05104.504710294.39105.3325 10314.4104.374510351.08106.211310369.67106.2117
#Mann= 3 , 0 , 0
9362.845  0.0739       09362.845  0.0739       010369.67  0.0739       0
#XS Ineff= 2 , 0
       09872.253                       0
Bank Sta=9362.845,10369.67
Exp/Cntr=0.3,0.1

Type RM Length L Ch R = 1 ,6043.406,191.955900,191.955900,191.955900
XS GIS Cut Line= 6
1204050.91526988610545.4165219221203614.24588612610249.810187638
1203588.59195688610238.1527648121203565.55576134610229.405363813
1203515.19222972610209.3506189581203198.23785466610202.605397865
#Sta/Elev= 30
9418.864108.0013 9482.94104.52279498.788102.61829520.828102.39769534.445100.7075
9589.91197.748799625.56997.875479731.51895.241779743.22396.238519784.04496.93212
 9815.7495.915979867.24496.298559901.24194.918479950.05996.184129964.473 98.6964
9971.68197.402589996.31795.9049210006.9496.7832910035.1696.4799210102.0698.87479
10131.5999.2603210151.2898.3574210174.25100.118910203.7999.64547 10236.6101.8821
10269.42100.612910295.67103.679110321.92101.456510348.18103.344110370.24102.7352
#Mann= 3 , 0 , 0
9418.864  0.0809       09418.864  0.0809       010370.24  0.0809       0
#XS Ineff= 2 , 0
       0 9833.12                       0
Bank Sta=9418.864,10370.24
Exp/Cntr=0.3,0.1

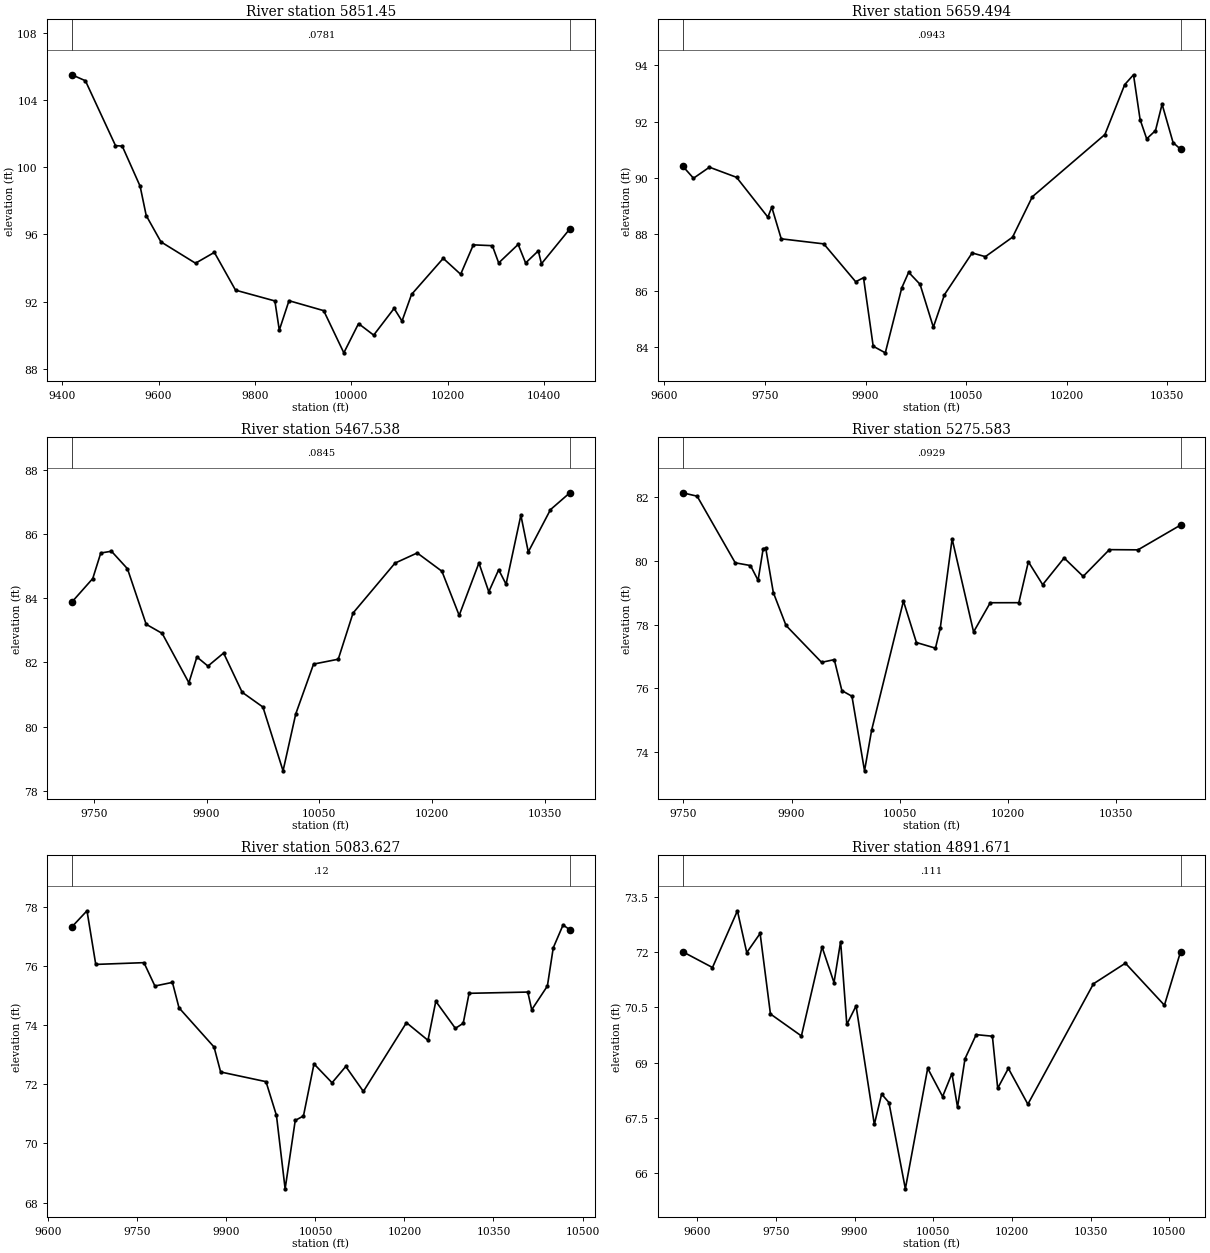
Type RM Length L Ch R = 1 , 5851.45,191.955900,191.955900,191.955900
XS GIS Cut Line= 6
 1204146.6239593610416.6448306441203794.48270473610205.864699587
1203734.58485118610163.4546549621203695.09139585610125.586039022
 1203641.4437592610046.0615338091203243.48196241  610018.1486509
#Sta/Elev= 30
9420.077105.49599448.163105.14089510.612101.28289524.636101.25199561.71698.86692
9574.34497.123289604.93395.55671  9676.794.286619715.81994.931389759.74592.68449
 9841.4292.041899850.63190.306449870.73192.056449942.76191.464789984.55888.95503
10015.07 90.694710046.5290.00818 10088.991.5990410105.3490.8451210125.0892.42827
10190.8694.5755310227.0393.6285910253.34 95.378510292.8195.3296910305.9794.30306
 10346.495.4052110361.88 94.300310388.1995.0204710394.7794.2550110453.7596.32943
#Mann= 3 , 0 , 0
9420.077  0.0781       09420.077  0.0781       010453.75  0.0781       0
#XS Ineff= 2 , 0
       09845.377                       0
Bank Sta=9420.077,10453.75
Exp/Cntr=0.3,0.1

Type RM Length L Ch R = 1 ,5659.494,191.955900,191.955900,191.955900
XS GIS Cut Line= 6
 1204077.0176397610110.3770243821203855.62093246609959.858248293
1203779.93684405609930.1800884311203725.26548856609922.177847758
1203680.82316431609905.7298914051203389.65523362609908.518697515
#Sta/Elev= 30
9626.96590.426369643.34789.98906 9667.1590.380719707.62190.020999754.30488.60695
 9760.1488.959839774.26687.836529837.742 87.65699885.349  86.3119897.01986.45528
 9911.4684.021219929.51183.786099954.06486.093159964.37886.647269981.36586.22003
10001.2184.6972110017.8385.8537410059.0987.3346210078.7987.2027310119.3787.89554
 10148.9 89.330810257.17 91.5414 10286.793.3134410299.8393.6639910309.6792.07275
10319.5191.3884510332.6491.6818910342.4892.6195710358.8891.2554410369.9791.02096
#Mann= 3 , 0 , 0
9626.965  0.0943       09626.965  0.0943       010369.97  0.0943       0
#XS Ineff= 2 , 0
       0                               0
Bank Sta=9626.965,10369.97
Exp/Cntr=0.3,0.1

Type RM Length L Ch R = 1 ,5467.538,191.955900,191.955900,191.955900
XS GIS Cut Line= 6
1204118.65047549609878.6235558351203915.03924178609793.981965114
1203883.90854019609783.6307301311203846.01045967609776.190486218
1203828.36704351609770.0254598951203476.66313311609784.967480227
#Sta/Elev= 30
9720.79883.880399748.57984.612959759.23885.40704 9773.4585.462829794.76884.91689
9819.63983.189149840.95782.904879876.48881.367589887.14782.170919901.85381.88753
9922.67782.29318 9947.3881.07246 9975.0180.6121710001.7878.62648 10018.780.39982
10042.3981.9492510075.2382.1012710094.9383.5390210150.7685.0926710180.3185.40878
10213.1584.8397210236.1483.4656510262.4185.0964910275.5484.2004510288.6884.88623
10298.5384.4363910318.2386.5836910328.0885.4401710357.6486.7579510383.4487.28229
#Mann= 3 , 0 , 0
9720.798  0.0845       09720.798  0.0845       010383.44  0.0845       0
#XS Ineff= 2 , 0
       0                               0
Bank Sta=9720.798,10383.44
Exp/Cntr=0.3,0.1

Type RM Length L Ch R = 1 ,5275.583,191.955800,191.955800,191.955800
XS GIS Cut Line= 6
1204141.40348536609684.0383168011203936.60751456609604.354552448
1203907.96442735609594.0269823971203906.07917285609593.359288171
1203840.35615307609563.9674154671203476.66313311609605.731207252
#Sta/Elev= 30
  9748.882.134959769.05782.028459821.86379.939729842.98679.853639853.54779.39073
9860.58880.380649864.10880.40134 9874.67 79.00829892.27277.975169941.55876.81983
 9959.1676.90399 9969.7175.932779983.66175.75613 10001.173.4181510010.9274.69124
10055.0178.73957   1007377.44108 10099.477.26403   1010677.8805410122.5180.69029
10152.2477.7726110175.3578.6877410214.9878.6892510228.1979.9722810248.0179.25442
10277.7380.0909810304.1579.5144710340.4780.35233 10380.180.3458310439.0881.12134
#Mann= 3 , 0 , 0
  9748.8  0.0929       0  9748.8  0.0929       010439.08  0.0929       0
#XS Ineff= 2 , 0
       0                10051.55       0
Bank Sta=9748.8,10439.08
Exp/Cntr=0.3,0.1

Type RM Length L Ch R = 1 ,5083.627,191.955900,191.955900,191.955900
XS GIS Cut Line= 6
1204292.79723048609572.6682054251204021.38021034 609432.84614256
1203971.09717897609413.3595165761203969.26303881609412.562064409
1203913.81731415609391.4888117761203497.54502901609433.455566213
#Sta/Elev= 30
9639.75877.333159665.21977.878639679.98276.062559761.17476.122199779.627 75.3313
9809.15275.454239820.22474.593389879.27373.265279890.345 72.42059966.78672.09255
9984.379 70.9501    999968.4637110016.0470.7803610029.88 70.931210047.6372.69386
10078.0772.0553110101.1672.6079110130.8371.7607310203.3874.0898410239.6573.49315
10252.8474.8138710285.8173.89778   1029974.06965 10308.975.0841110407.8275.12647
10414.4274.52689 10440.875.3303810450.6976.6249710467.1877.39612 10478.777.23717
#Mann= 3 , 0 , 0
9639.758    0.12       09639.758    0.12       0 10478.7    0.12       0
#XS Ineff= 2 , 0
       0                10086.78       0
Bank Sta=9639.758,10478.7
Exp/Cntr=0.3,0.1

Type RM Length L Ch R = 1 ,4891.671,302.433000,302.433000,302.433000
XS GIS Cut Line= 6
1204390.24607795609440.4161981791204127.07739431609266.105965674
1204022.02734652 609228.944142551204020.12997988609228.311687052
1203890.82073474609174.1720256811203521.90724087609266.400399163
#Sta/Elev= 30
 9571.91 72.0144 9629.0571.584179676.59373.122619694.40571.98739 9719.8872.50817
9739.55670.323759798.58569.727869837.93772.141729860.76171.174459873.35572.28868
 9885.16 70.03919902.83970.54322 9937.6467.32856 9951.5668.150799965.48167.92264
9996.80165.5814210039.3868.8499310067.8368.0843210085.6268.7083510096.2967.79451
10110.5169.1091310131.8569.7631910162.7569.7208110172.8968.3090710193.1968.84831
10230.3967.8764210355.5171.1430910416.3871.7010710490.7870.5610410521.4572.00788
#Mann= 3 , 0 , 0
 9571.91   0.111       0 9571.91   0.111       010521.45   0.111       0
#XS Ineff= 2 , 0
       0                10117.14       0
Bank Sta=9571.91,10521.45
Exp/Cntr=0.3,0.1

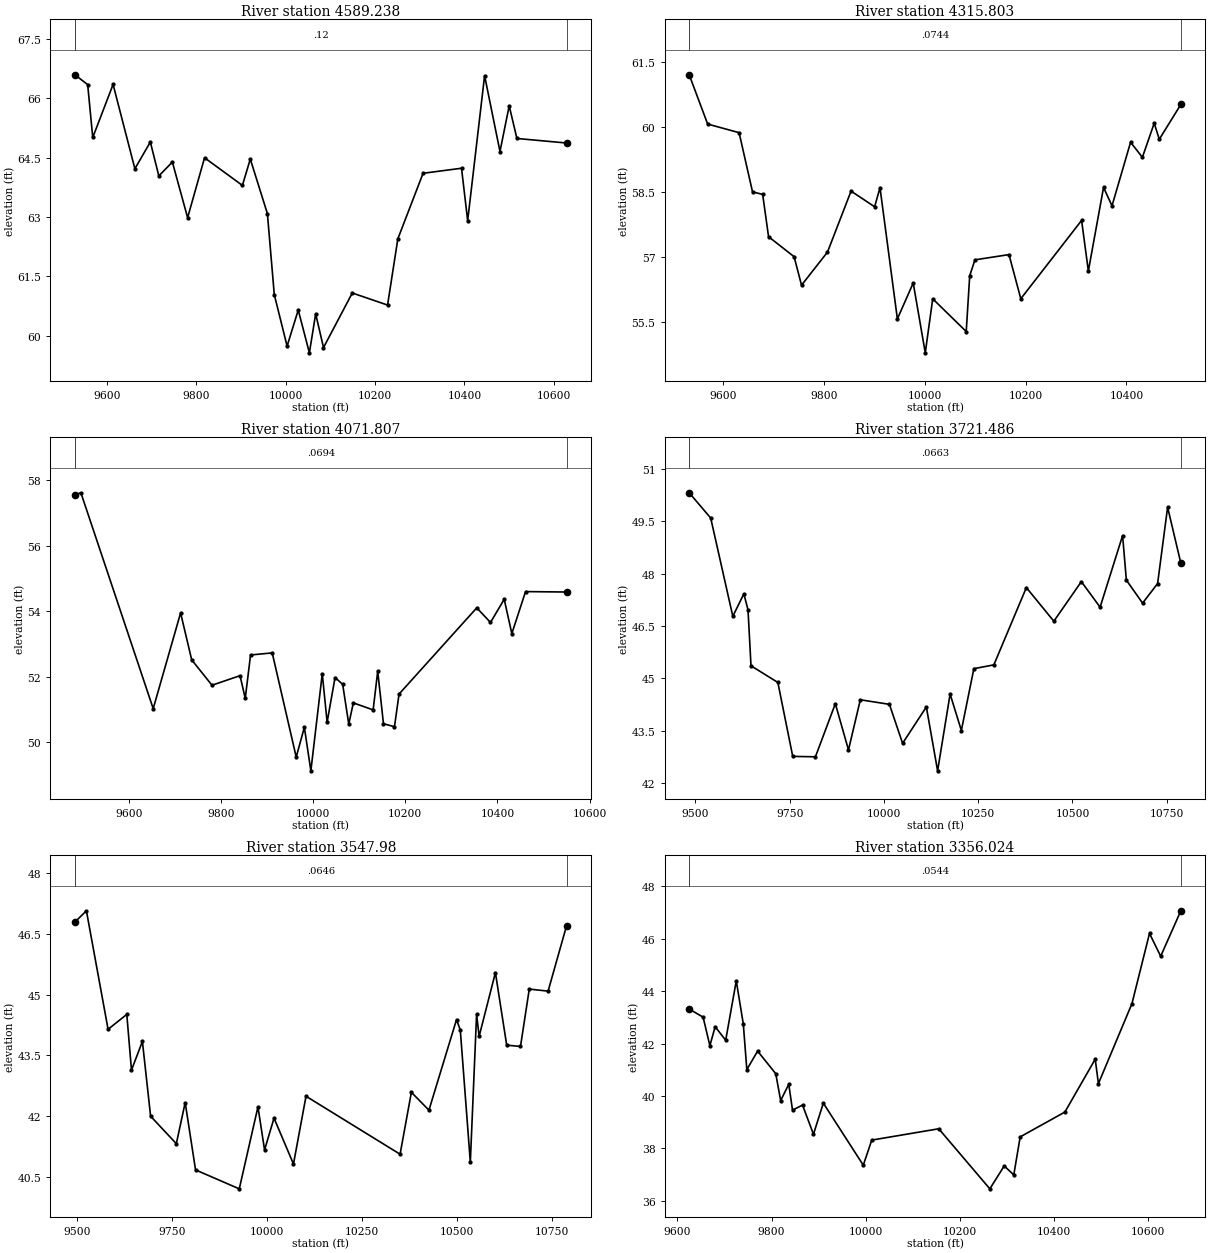
Type RM Length L Ch R = 1 ,4589.238,273.434700,273.434700,273.434700
XS GIS Cut Line= 6
  1204557.301245609174.1720256811204262.89101553609003.901051134
1204046.10936004608914.2965800911203996.97037217608904.447537199
1203856.01757497608911.4081691651203537.56866279609012.337332577
#Sta/Elev= 30
  9528.666.591859557.10166.343329568.47165.007079613.95166.348069662.71864.21699
9697.33164.893259716.28164.035249746.60164.386419780.71262.980479818.61264.49484
9903.29263.795849920.96964.461789959.21963.083949974.63261.03572 10003.359.73431
10028.2560.6464610053.1859.5645910067.2160.5501410084.7559.6977810149.1961.07681
 10228.160.77219 10251.162.4461510307.5364.1020110393.5764.2301310407.3462.90434
 10445.266.5694210479.6164.6528710500.2665.8068310517.4764.9818810628.6264.86763
#Mann= 3 , 0 , 0
  9528.6    0.12       0  9528.6    0.12       010628.62    0.12       0
#XS Ineff= 2 , 0
       0                10235.63       0
Bank Sta=9528.6,10628.62
Exp/Cntr=0.3,0.1

Type RM Length L Ch R = 1 ,4315.803,243.996100,243.996100,243.996100
XS GIS Cut Line= 6
1204550.34061301608928.8097490521204238.16899654608728.570642084
1204189.63223347608713.0109839291204095.92221451 608676.66009827
1204038.94366345608657.3771814111203654.15924811608737.392370149
#Sta/Elev= 30
 9532.5861.199939569.21260.062189631.57759.864039658.24158.49722 9678.3558.43991
9690.04357.463199740.71457.001759755.46756.344259806.976 57.1073 9853.7558.51544
9900.523 58.15359911.19958.594249945.652 55.56549977.10256.39467   1000154.78276
 10015.856.0292810082.2755.27439 10089.256.5635510099.5956.9289810167.11   57.05
10190.5756.0312910311.2157.8387310324.6156.6718410354.7758.6010610371.5258.17512
10408.3959.6425210431.8459.29503 10455.360.0828610465.3559.7110110508.1160.51452
#Mann= 3 , 0 , 0
 9532.58  0.0744       0 9532.58  0.0744       010508.11  0.0744       0
#XS Ineff= 2 , 0
       09903.598                       0
Bank Sta=9532.58,10508.11
Exp/Cntr=0.3,0.1

Type RM Length L Ch R = 1 ,4071.807,350.320800,350.320800,350.320800
XS GIS Cut Line= 6
1204654.75009245608732.1718961751204332.24409169 608505.84276104
1204263.34318516 608483.507774041204216.04226568608464.441850707
1204178.31637529608449.7395987961203673.30098602608514.652147397
#Sta/Elev= 30
9483.02257.557619495.93857.618199652.90151.025659712.37653.949199736.42552.51578
9780.51551.740499841.37652.032399852.66151.339079864.22152.664629911.24252.72797
9963.30749.545169980.97450.456359995.10749.1256410019.8452.09028 10030.450.61105
10047.5851.9763710064.12 51.767710077.3550.5548810087.2751.2010910130.2750.98699
 10140.252.1687410152.6750.5643910176.58 50.472810186.5151.47088 10355.254.10413
10384.9853.6569610414.75 54.366110431.2853.3164610461.0654.5999910550.1154.58718
#Mann= 3 , 0 , 0
9483.022  0.0694       09483.022  0.0694       010550.11  0.0694       0
#XS Ineff= 2 , 0
       09888.865                       0
Bank Sta=9483.022,10550.11
Exp/Cntr=0.3,0.1

Type RM Length L Ch R = 1 ,3721.486,173.506600,173.506600,173.506600
XS GIS Cut Line= 6
1204780.04146773608387.620614126  1204553.374441608234.640687391
1204466.60616168608199.3342487961204353.32716727608158.534792513
1204282.46689245608131.0206839891203549.74976867608237.967026979
#Sta/Elev= 30
9483.54850.311029540.58149.588499599.22846.776169628.55147.420769639.54446.96227
 9647.46 45.36189718.70644.884049758.15342.769199818.36842.757189871.17644.27649
9906.04842.953779937.43244.3886710014.5844.2585710049.5943.1431810112.5944.18392
10142.4342.3556510175.5844.5518310205.42 43.509710238.5845.2786610291.6345.38753
10377.8347.5986510450.7846.6360910523.7247.7694310573.4547.0378510633.1449.08679
10643.0847.8113310686.1947.1536210725.9747.71423 10752.549.8978610787.5848.29757
#Mann= 3 , 0 , 0
9483.548  0.0663       09483.548  0.0663       010787.58  0.0663       0
#XS Ineff= 2 , 0
       09874.252        10054.08       0
Bank Sta=9483.548,10787.58
Exp/Cntr=0.3,0.1

Type RM Length L Ch R = 1 , 3547.98,191.955900,191.955900,191.955900
XS GIS Cut Line= 6
 1204799.1832056608262.3292388471204637.41392446608140.485881731
1204439.02359864608012.3539562231204395.48208475607988.677153394
1204338.26685068607966.5477928221203598.47419241608051.770122036
#Sta/Elev= 30
9494.95346.791799525.14247.070259582.21744.145689631.50544.513039643.82743.13816
9672.57843.845359694.19242.001229761.92741.322869785.24242.338329812.52740.67546
 9927.6540.20853 9976.8442.230199994.23741.1697610019.1641.9531410070.3540.82049
10103.38 42.493610351.0741.0628510380.7942.5914610427.0342.1499810499.6844.38505
10509.5944.1262810536.0140.8686310552.5244.5176710559.1343.9702210602.0645.54439
10631.7843.7537810668.1143.7224210691.2345.1380110740.7745.0871210789.4246.70169
#Mann= 3 , 0 , 0
9494.953  0.0646       09494.953  0.0646       010789.42  0.0646       0
#XS Ineff= 2 , 0
       09864.698        10050.11       0
Bank Sta=9494.953,10789.42
Exp/Cntr=0.3,0.1

Type RM Length L Ch R = 1 ,3356.024,191.955800,191.955800,191.955800
XS GIS Cut Line= 6
1204836.92347185608081.1653389091204671.27395359 607987.06807028
1204556.52177479607901.3907506741204514.53090832607859.823813635
1204456.37208155607827.2897413071203890.82073474607679.376312122
#Sta/Elev= 30
9625.16943.31486 9654.7443.00447 9669.0841.916359680.29242.640559702.68842.12403
9725.14144.392239740.09142.746369747.56641.003899770.46441.710119809.02540.84828
9819.43239.822649836.65140.444689844.604 39.45739865.87939.65097  9889.138.53651
9910.01539.725599994.91437.3573110012.9338.31452 10155.238.7468510263.7236.45497
10294.2437.3291610314.5836.9870910328.1538.43718 10423.139.3844810487.5441.40191
10494.3240.4695910565.5343.5197910602.8446.1998210626.57 45.328610669.3847.06402
#Mann= 3 , 0 , 0
9625.169  0.0544       09625.169  0.0544       010669.38  0.0544       0
#XS Ineff= 2 , 0
       09945.078        10190.47       0
Bank Sta=9625.169,10669.38
Exp/Cntr=0.3,0.1

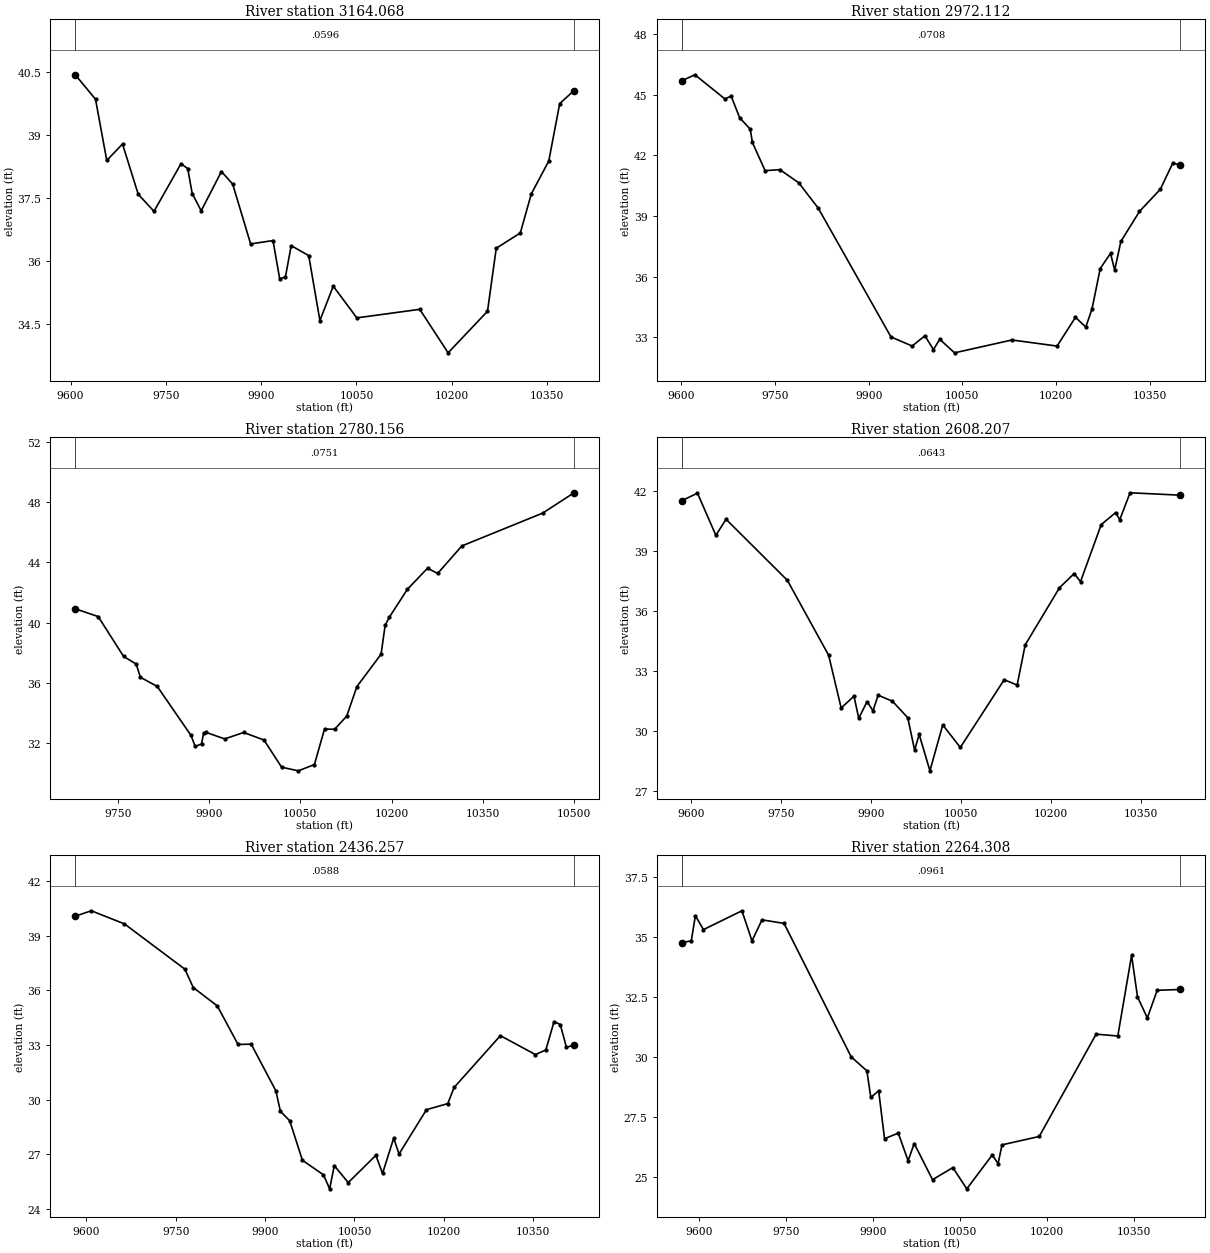
Type RM Length L Ch R = 1 ,3164.068,191.955900,191.955900,191.955900
XS GIS Cut Line= 6
1204965.69611006607842.4123365441204716.42632476607741.493740011
1204602.03488369 607697.362186681204578.70139203607688.738368615
1204424.58469227607634.6387559491204229.04499873607572.043057609
#Sta/Elev= 30
9607.46740.422119639.31939.839259657.01738.383989681.79338.77406 9706.5737.57799
9731.34737.172759773.82138.305359784.43938.190359791.51837.596439805.67637.18604
9837.53238.12021 9855.2337.820749883.49936.396579918.66436.477759929.21435.56782
9938.23535.61007 9947.3536.356929974.92936.118959992.51134.5732110013.5335.39221
10050.67 34.637610149.7234.8410310194.3433.8056410256.3434.7945710270.1236.29518
10308.0236.6583210325.2437.58571 10352.838.3707710370.0239.7360410392.5340.04632
#Mann= 3 , 0 , 0
9607.467  0.0596       09607.467  0.0596       010392.53  0.0596       0
#XS Ineff= 2 , 0
       09956.772                       0
Bank Sta=9607.467,10392.53
Exp/Cntr=0.3,0.1

Type RM Length L Ch R = 1 ,2972.112,191.955900,191.955900,191.955900
XS GIS Cut Line= 6
1205054.79010765607613.6127737351204909.73291769607572.867789467
1204718.00561364607531.315386518 1204634.0845576607508.049156321
1204436.17249052607505.9647175151204271.21363093607481.311923856
#Sta/Elev= 30
9600.49245.68201 9621.5645.977739669.48244.787859679.66944.921729693.25243.85326
 9710.2343.288749713.62642.63488    973441.239719757.69541.289799787.90840.64033
 9819.1439.386359935.61633.024549969.53632.57348    999033.0802410003.6632.39946
10013.8432.9057810037.4932.2372810129.4632.8729210201.68 32.571910231.2333.99202
10247.7433.5124810257.6534.3989910270.8636.4029610287.3837.1518910293.9936.32287
 10303.937.7398110333.7439.2246610367.1240.3187910387.1441.6167510399.4241.50715
#Mann= 3 , 0 , 0
9600.492  0.0708       09600.492  0.0708       010399.42  0.0708       0
#XS Ineff= 2 , 0
       0                               0
Bank Sta=9600.492,10399.42
Exp/Cntr=0.3,0.1

Type RM Length L Ch R = 1 ,2780.156,171.949500,171.949500,171.949500
XS GIS Cut Line= 3
1204899.74527994607461.9333810811204558.77299106607345.553617805
1204104.48356423607272.050609395
#Sta/Elev= 30
9679.70940.919299717.48540.397629759.08637.752729779.88637.243189786.81936.36466
9814.55235.752069870.01932.500299876.95231.759079887.35231.928189890.81932.63268
9894.28632.704619925.48632.261489956.68632.690329990.24932.1863210019.0930.38196
10046.5430.1379710073.1330.5562710089.7432.9206510106.3632.90155 10126.3 33.7815
10142.9235.73875 10182.837.9001210189.4539.81533 10196.140.3450510226.0142.21317
10259.2443.6194410275.86 43.269110315.7445.1018610448.6847.2851310500.1948.63727
#Mann= 3 , 0 , 0
9679.709  0.0751       09679.709  0.0751       010500.19  0.0751       0
#XS Ineff= 2 , 0
       0                               0
Bank Sta=9679.709,10500.19
Exp/Cntr=0.3,0.1

Type RM Length L Ch R = 1 ,2608.207,171.949500,171.949500,171.949500
XS GIS Cut Line= 6
1205017.16727247607338.408179573 1204766.2683231607264.012881312
1204713.48634375607240.0294328271204645.95050207607200.310820371
1204484.59260016607124.007600979 1204242.4009463607041.679365885
#Sta/Elev= 30
 9583.7541.49483 9609.9741.873359640.66839.765739657.72340.567059760.04937.51315
9828.93933.766979849.86831.126489871.25931.719129879.18930.614799893.11231.44703
9902.98230.987139911.56131.767739935.43131.467729961.04130.640799972.459 29.0185
9980.07129.807769998.04327.9845910019.4130.28246 10048.829.1532810122.0232.54366
10143.6532.2737210157.0234.2826810214.2937.1424410238.8637.8524810249.3937.44416
10283.9640.3005310308.0440.9008210314.9340.5446810332.1341.8924210416.29 41.7722
#Mann= 3 , 0 , 0
 9583.75  0.0643       0 9583.75  0.0643       010416.29  0.0643       0
#XS Ineff= 2 , 0
       0                               0
Bank Sta=9583.75,10416.29
Exp/Cntr=0.3,0.1

Type RM Length L Ch R = 1 ,2436.257,171.949400,171.949400,171.949400
XS GIS Cut Line= 6
 1205128.8007531607248.0179327951204876.29288928607151.643940188
1204807.96716455607114.2043990511204688.49504204 607035.63330613
1204591.86239773606985.6642493761204369.72897392606903.564889887
#Sta/Elev= 30
9581.43440.060689608.28840.355889663.99139.636469765.31837.154629779.43536.14844
9819.87435.136899854.59933.027719876.70433.041359918.10230.484619925.69329.36276
9941.32828.844359962.68726.675959998.02925.8769810008.35 25.1102 10016.2 26.3803
 10039.625.4530610085.9126.9463810097.1425.9534610115.8527.8838110124.8527.02164
10170.8629.4502710206.6529.78425 10217.330.6699310294.9633.5083710353.8932.47001
10371.2232.7263710385.0834.2820410395.4834.1187210405.8832.8632310418.5433.00545
#Mann= 3 , 0 , 0
9581.434  0.0588       09581.434  0.0588       010418.54  0.0588       0
#XS Ineff= 2 , 0
       0                               0
Bank Sta=9581.434,10418.54
Exp/Cntr=0.3,0.1

Type RM Length L Ch R = 1 ,2264.308,171.949500,171.949500,171.949500
XS GIS Cut Line= 6
1205204.22967727607046.984569895 1205046.0284889606990.246161898
1204832.86149035606932.3753149371204747.30014295606899.969792716
 1204559.4784046 606853.689426751204379.01673752606804.436446722
#Sta/Elev= 30
9569.49434.752489585.98434.823029592.99535.870139607.01635.292159673.39336.07628
9690.72734.825329708.06135.698039746.08535.550429862.00429.991059889.10229.40842
9895.87628.302749909.42428.575839919.58626.582869943.29626.814629960.29325.66314
9970.81626.3808710002.4424.8755910037.4925.3782110061.5924.4939610105.5225.90409
10115.6625.5459610122.4126.3264910186.6226.6748710284.8730.9372510322.2830.86003
10346.0934.2162710356.2932.4949310373.2931.61193 10390.332.76409 10430.532.79862
#Mann= 3 , 0 , 0
9569.494  0.0961       09569.494  0.0961       0 10430.5  0.0961       0
#XS Ineff= 2 , 0
       0                               0
Bank Sta=9569.494,10430.5
Exp/Cntr=0.3,0.1