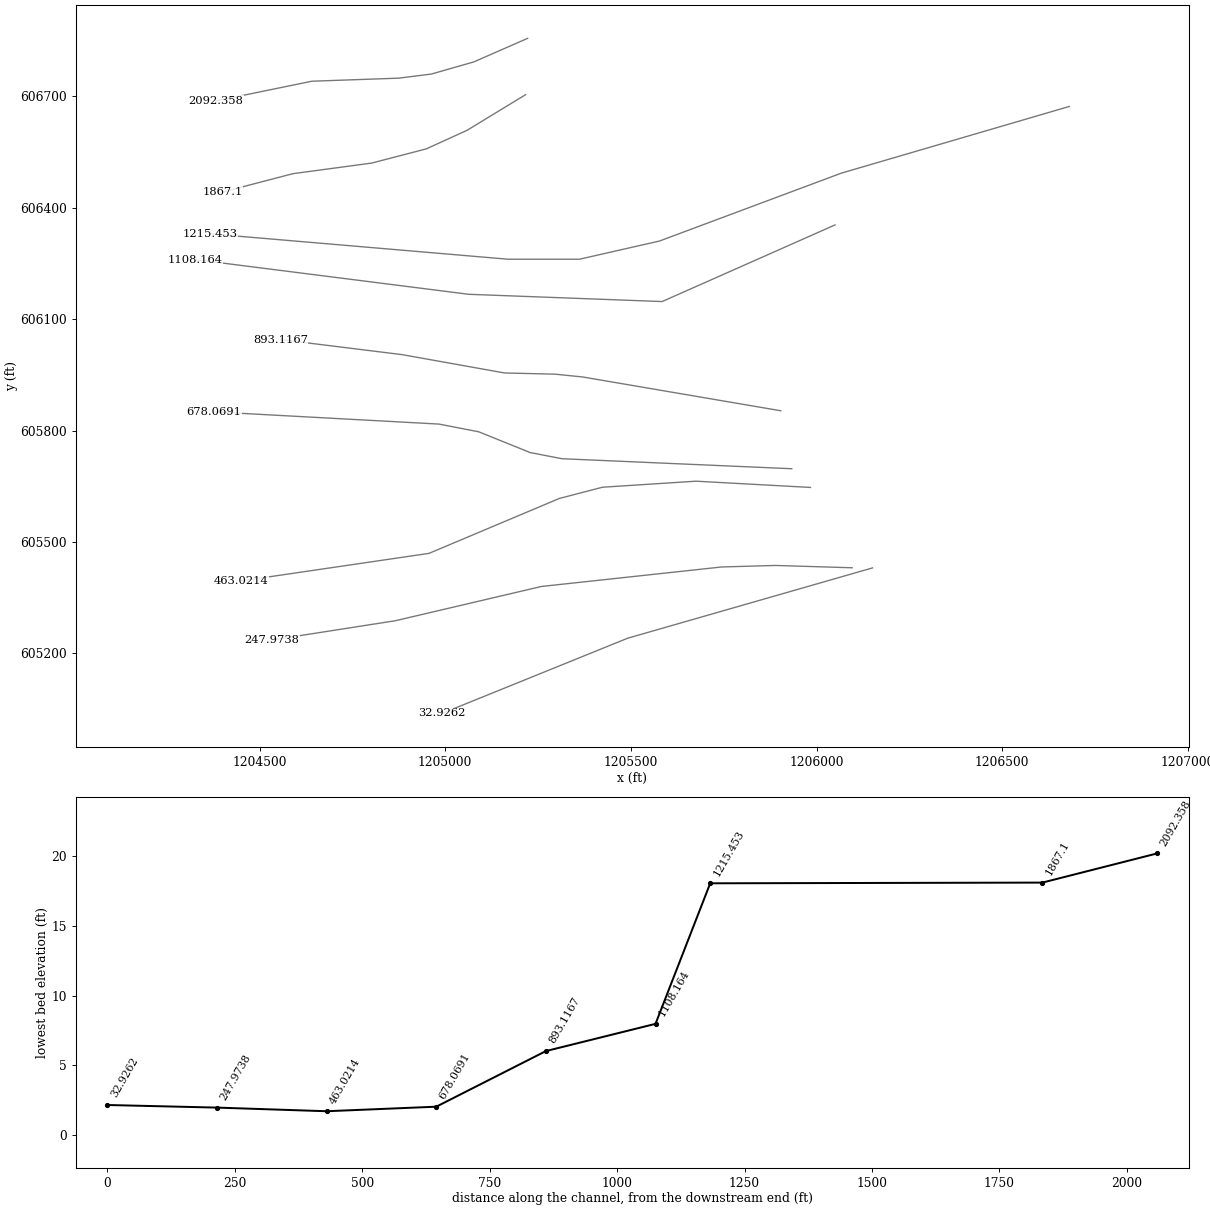
HEC-RAS study 39_ras.prj: 39

--- 39_ras.g01 (geometry) --- (continued)

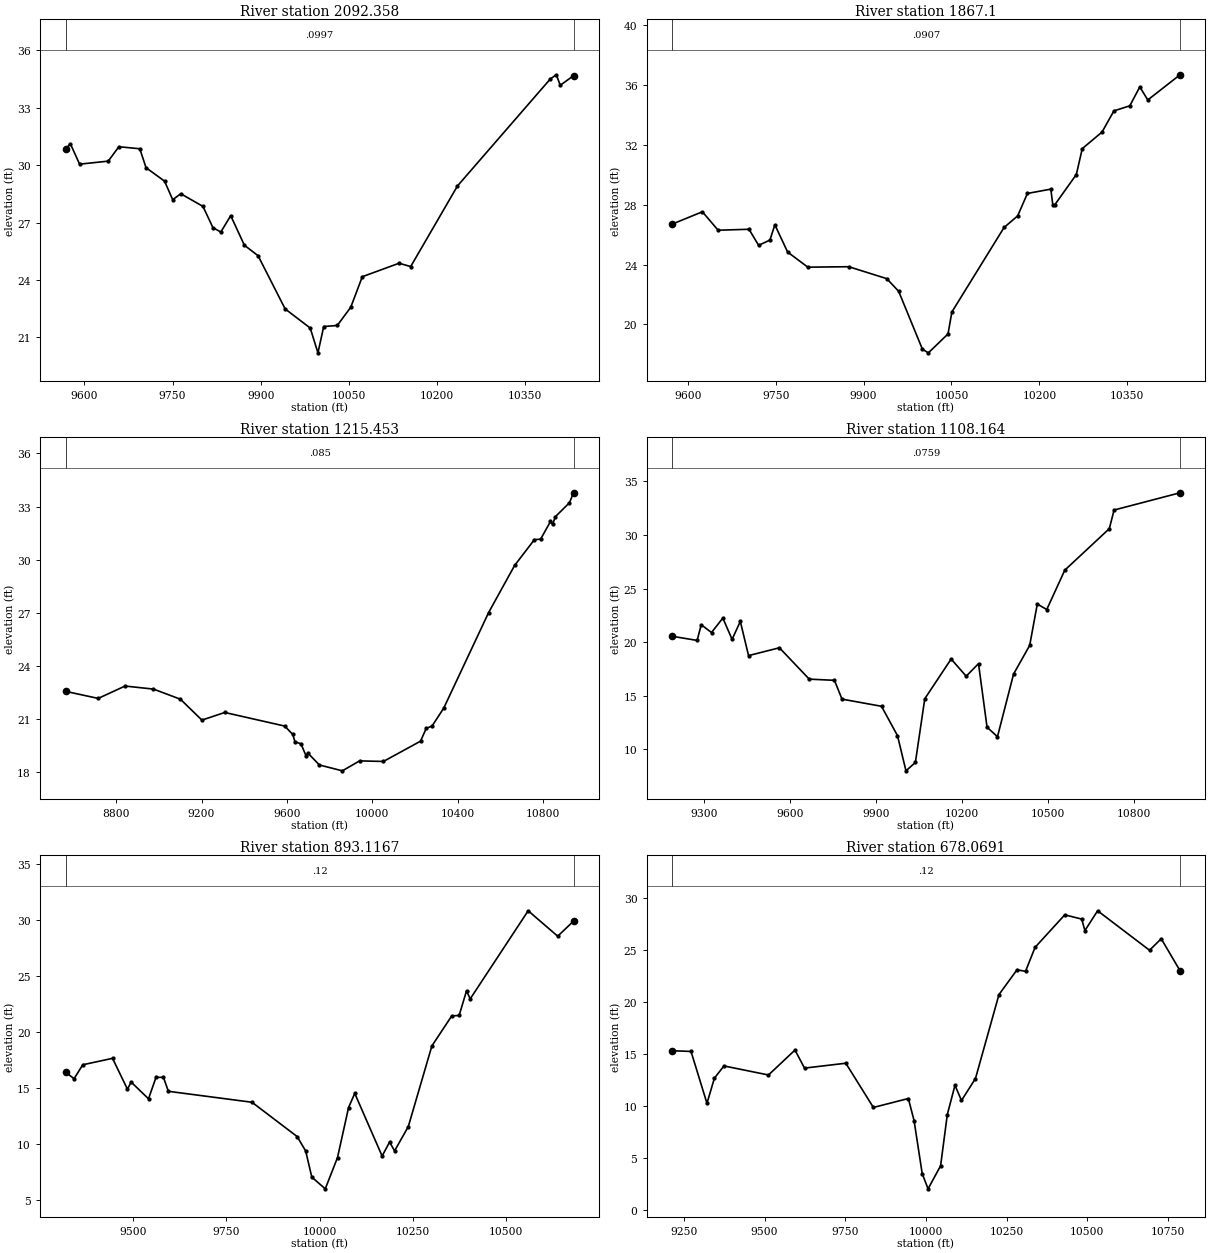
Type RM Length L Ch R = 1 ,2092.358,225.258500,225.258500,225.258500
XS GIS Cut Line= 6
1205222.05781972606856.5417445741205076.82868164606792.962752159
1204962.93141162606760.4035886391204875.06784781606749.321525922
1204641.04145892606741.0576669451204382.67751868606687.966860382
#Sta/Elev= 30
9567.99630.849079576.25231.125639591.96330.058249640.71130.216919658.76530.96959
9694.34630.86371 9704.9429.874479736.48529.169769750.27828.202149764.07128.51216
9801.82927.849439818.68726.740419832.174 26.51219848.974 27.36619872.22625.82058
9895.46425.274829941.541  22.4939984.19421.493469997.31920.1978610007.1621.57353
10030.1321.6274210053.0922.5775710072.7824.1766210135.2824.8804710155.0724.70741
10234.6628.9209810392.57 34.512710402.6934.7296410409.43 34.181510432.0434.68087
#Mann= 3 , 0 , 0
9567.996  0.0997       09567.996  0.0997       010432.04  0.0997       0
#XS Ineff= 2 , 0
       0                               0
Bank Sta=9567.996,10432.04
Exp/Cntr=0.3,0.1

Type RM Length L Ch R = 1 ,  1867.1,651.646500,651.646500,651.646500
XS GIS Cut Line= 6
1205216.70421329606704.9168676321205058.92064484606608.864835949
1204949.28933053606558.8911209431204802.17959502606520.649671273
1204589.72251956606492.0260178271204400.95491336 606442.72177142
#Sta/Elev= 30
9572.99826.701279624.87527.532069651.76226.30073 9704.4626.363259720.899 25.2905
9740.10325.641579748.62626.660339770.31224.843459804.78823.830219874.80523.86023
9939.57823.062449959.862 22.215910000.4318.3436810010.5918.1048510044.0919.36814
10050.6820.8364210139.7526.4822410162.9427.2559510179.59 28.757710219.56 29.0463
10222.8928.0035510226.2227.9959210263.0930.0230610273.2131.7532610306.9532.86153
10327.1934.2749610354.3334.6143610371.3835.8791510385.0135.0048210440.0136.68846
#Mann= 3 , 0 , 0
9572.998  0.0907       09572.998  0.0907       010440.01  0.0907       0
#XS Ineff= 2 , 0
       0                               0
Bank Sta=9572.998,10440.01
Exp/Cntr=0.3,0.1

Type RM Length L Ch R = 1 ,1215.453,107.288900,107.288900,107.288900
XS GIS Cut Line= 6
1206680.51059204 606673.058098571206066.77970979606493.509170234
1205577.10081434606310.6957159491205361.64210039606261.727826416
1205169.03506812606261.7278264161204365.96167961606330.282871783
#Sta/Elev= 30
8562.25822.550118715.61922.149978841.45422.84971 8974.7722.676579101.209  22.103
9201.714 20.9228 9308.9121.354759590.04820.58581 9627.5720.11383  9638.119.69466
9666.11619.58264 9690.6318.882679697.63419.068499752.51718.385589860.181 18.0542
9940.92918.6172710052.5918.5847510226.7219.7319910253.0420.4495710280.9220.59339
10335.2921.5968610545.9427.0075210667.8629.6708110760.1231.1230910789.7831.15932
10835.91 32.1548 10845.831.9942510858.9832.4285310924.8833.2161210943.9933.77858
#Mann= 3 , 0 , 0
8562.258   0.085       08562.258   0.085       010943.99   0.085       0
#XS Ineff= 2 , 0
       09782.494        10042.55       0
Bank Sta=8562.258,10943.99
Exp/Cntr=0.3,0.1

Type RM Length L Ch R = 1 ,1108.164,215.047600,215.047600,215.047600
XS GIS Cut Line= 4
1206049.85330558606354.0744774191205584.22520468606147.714424327
1205063.42699179606167.2513119131204327.34371972606260.662894666
#Sta/Elev= 30
 9189.4120.542219277.15420.154189291.50821.613279327.39420.891549366.86922.24106
9399.166 20.25069427.87521.928459456.58418.734959564.24219.466229668.31116.53837
9756.26116.427349782.52614.672279920.41814.002979976.23111.2575410005.787.976414
10038.618.75934110071.4414.7099810163.3718.41617 10215.916.8124210258.8617.98388
10288.6312.0523910325.0111.1620910381.2317.0176110437.4519.6907910463.9123.54933
10496.9823.0384210559.8126.7108710715.2530.5882110731.7932.3265110961.8733.93847
#Mann= 3 , 0 , 0
 9189.41  0.0759       0 9189.41  0.0759       010961.87  0.0759       0
#XS Ineff= 2 , 0
       0 9844.86        10059.91       0
Bank Sta=9189.41,10961.87
Exp/Cntr=0.3,0.1

Type RM Length L Ch R = 1 ,893.1167,215.047600,215.047600,215.047600
XS GIS Cut Line= 6
1205903.71223487605853.6274228481205370.18903767605944.634469093
1205296.56988425605952.1149522921205159.65527883605955.450629914
1204884.13355352606004.7629605031204556.07214231606045.402764154
#Sta/Elev= 30
9318.61616.439229341.60415.843679364.90217.087059444.77917.661049484.71814.91016
9494.70215.542379541.29714.052449561.26715.956559581.23615.974419594.549 14.7214
 9818.8513.744319939.91210.687429962.8789.3988529979.2827.07001310015.386.023779
10048.248.81141810077.92  13.27410094.52 14.535710167.918.94832110187.9610.19771
10201.329.40855910238.0711.5691110301.4118.7678410354.5921.4414310374.4621.48445
10394.33 23.675410404.2622.9667310559.7130.8190310638.9628.5515810681.41 29.8987
#Mann= 3 , 0 , 0
9318.616    0.12       09318.616    0.12       010681.41    0.12       0
#XS Ineff= 2 , 0
       0                10099.51       0
Bank Sta=9318.616,10681.41
Exp/Cntr=0.3,0.1

Type RM Length L Ch R = 1 ,678.0691,215.047700,215.047700,215.047700
XS GIS Cut Line= 6
1205933.26679314605697.5168023361205314.50029828605724.486561434
1205228.83484428605741.0861188781205090.21903217605797.023033748
1204983.37944786605817.7476101111204375.98707708605850.744212135
#Sta/Elev= 30
9212.99615.330329272.01615.258789321.43210.264939344.49312.689489374.08413.86443
9512.04712.993329594.09615.393469623.62413.655499751.57914.125389837.0269.868214
9945.33510.729799963.1018.5964889988.3053.49686810006.462.03598910045.254.255302
10066.069.18465210089.7612.0027410109.97 10.540310153.3312.6533810226.0620.72979
10282.0523.1205110308.3622.9679410337.9525.2782510429.9428.4068510482.4827.99935
10492.3326.8933210531.7328.7981510692.6324.9982110728.7526.1092710787.0223.03527
#Mann= 3 , 0 , 0
9212.996    0.12       09212.996    0.12       010787.02    0.12       0
#XS Ineff= 2 , 0
       0                               0
Bank Sta=9212.996,10787.02
Exp/Cntr=0.3,0.1

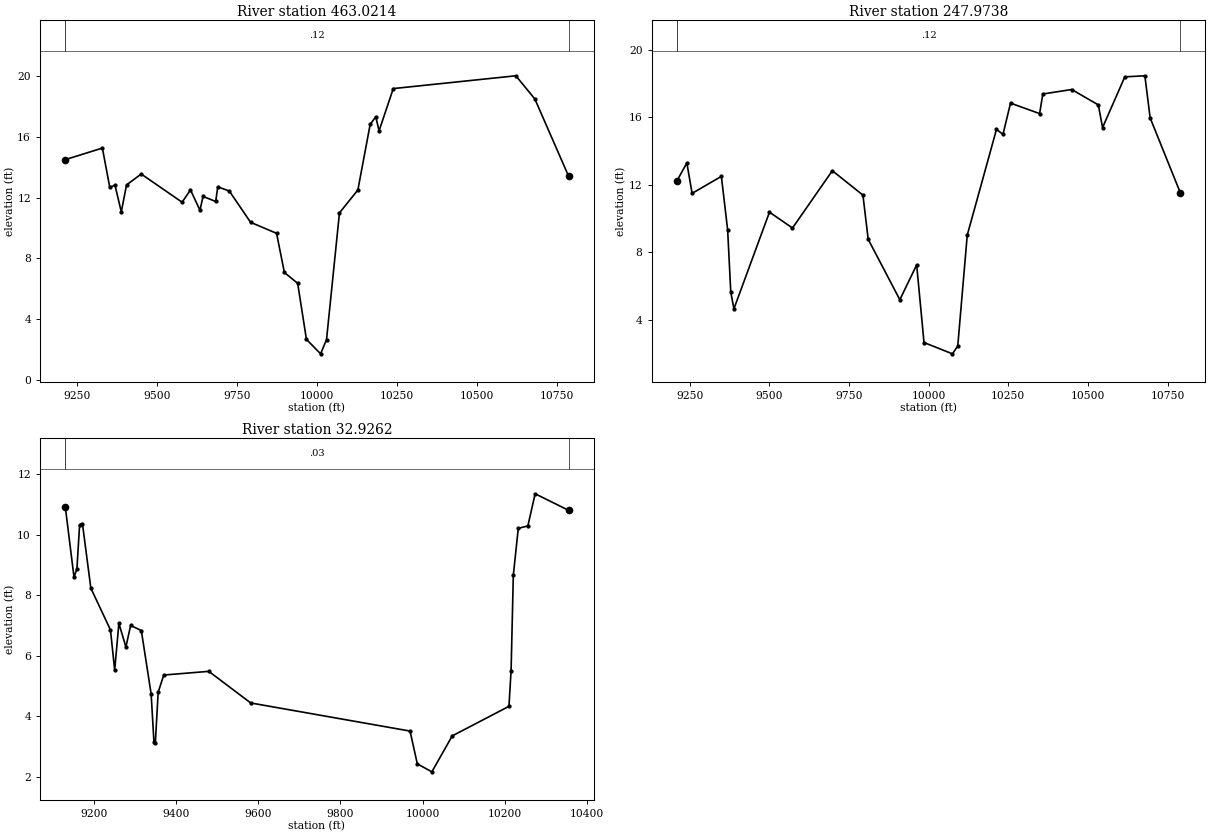
Type RM Length L Ch R = 1 ,463.0214,215.047600,215.047600,215.047600
XS GIS Cut Line= 6
  1205983.773318605647.1438416561205675.48147297605663.992872261
1205423.54806529605647.7087423651205307.43769251605617.476005439
1204956.39503204605469.5922275841204450.41596789 605395.36673213
#Sta/Elev= 30
9212.17214.502539328.371 15.26469351.40712.683239367.86112.816149387.55911.05967
9403.97112.838059449.92313.554469577.91511.697849604.167 12.50739633.73411.17177
 9643.5912.078349683.05111.74581 9689.6412.714439725.88112.429939792.29610.37408
9873.625  9.64869898.071 7.069979939.6686.3567919967.091 2.6649410011.521.709925
10030.042.648753 10070.510.9946310128.1312.5024610166.6116.81941 10184.117.32877
10194.5516.4026310238.9319.1834810622.7320.02659 10682.218.4962510787.8213.41475
#Mann= 3 , 0 , 0
9212.172    0.12       09212.172    0.12       010787.82    0.12       0
#XS Ineff= 2 , 0
       0                               0
Bank Sta=9212.172,10787.82
Exp/Cntr=0.3,0.1

Type RM Length L Ch R = 1 ,247.9738,215.047600,215.047600,215.047600
XS GIS Cut Line= 6
 1206095.9528949605430.8211428161205889.55839732605437.064721651
 1205744.7716454   605432.9971641205259.13596193605380.444218569
1204866.09124117605288.2440690111204534.10593977605236.395760446
#Sta/Elev= 30
 9210.0412.219829241.25213.282769257.67611.479129349.59112.485389369.2799.308794
9379.1235.6152999388.9674.6395939500.55310.366089572.7959.425583  9697.912.82181
 9793.9111.374469810.4658.7549849909.7985.1759539962.5787.2405339985.6252.640305
10074.871.97041410091.562.43125310121.339.00171810213.1715.2735610233.4914.97118
10257.2116.8267410348.4916.2054110358.5717.3665610449.2917.63254 10532.8 16.7206
10546.1115.3768110615.9318.38273 10678.918.4464510695.4515.9520810789.9611.52487
#Mann= 3 , 0 , 0
 9210.04    0.12       0 9210.04    0.12       010789.96    0.12       0
#XS Ineff= 2 , 0
       0                               0
Bank Sta=9210.04,10789.96
Exp/Cntr=0.3,0.1

Type RM Length L Ch R = 1 , 32.9262,0.000000,0.000000,0.000000
XS GIS Cut Line= 3
1206150.82659996605430.4612676071205491.39235414605241.118761377
1204991.91988075605038.718151273
#Sta/Elev= 30
9130.21610.930369151.4738.5970549158.519 8.868919165.12610.327079171.95310.36993
9192.4348.2325369240.2216.8509049250.4615.5195059260.7027.0675959277.7696.287105
9289.2876.9992889315.3166.830622 9339.214.7334689346.0363.141116 9349.453.117137
9356.2774.788602 9369.935.3586779479.4965.4807319581.5614.4351019969.3333.505315
9987.0332.42085710022.432.15702810071.993.34568410210.05 4.3237410215.255.501815
10220.67 8.6543710232.7210.2096410256.0710.2903710273.7711.3536510355.2210.80636
#Mann= 3 , 0 , 0
9130.216    0.03       09130.216    0.03       010355.22    0.03       0
#XS Ineff= 2 , 0
       09921.429        10073.34       0
Bank Sta=9130.216,10355.22
Exp/Cntr=0.3,0.1